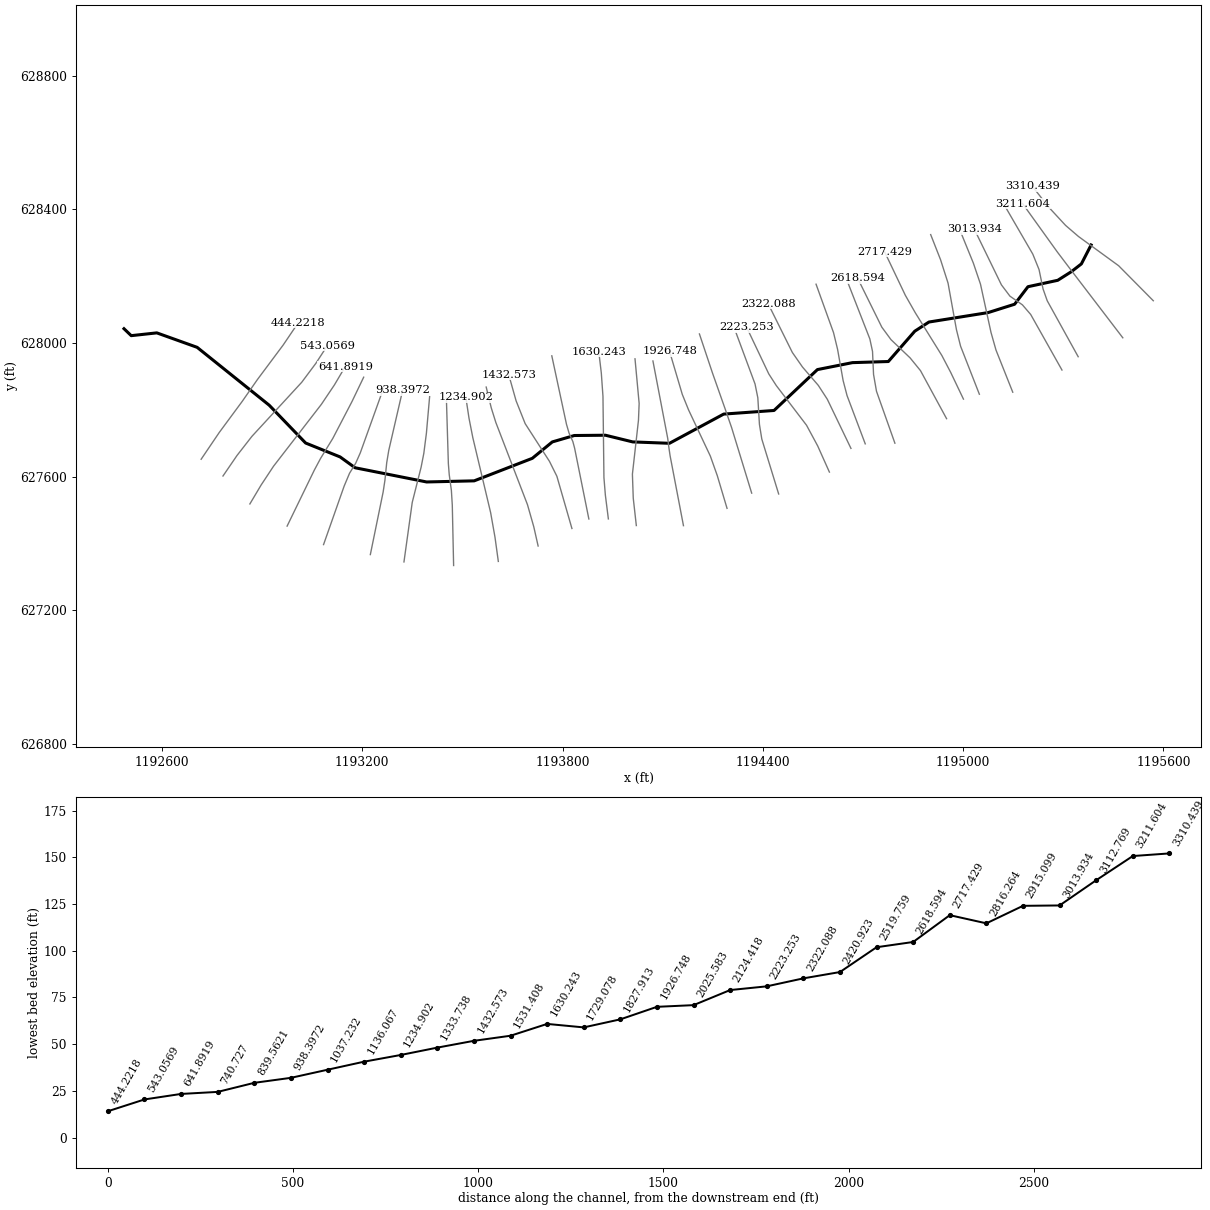
--- 386_ras.prj (project) ---

Proj Title=386
Current Plan=p01
Default Exp/Contr=0.3,0.1
English Units
Geom File=g01
Flow File=f01
Plan File=p01
Y Axis Title=Elevation
X Axis Title(PF)=Main Channel Distance
X Axis Title(XS)=Station
BEGIN DESCRIPTION:
RFD model 386 exported to HEC-RAS
END DESCRIPTION:

--- 386_ras.p01 (plan) ---

Plan Title=Plan 01
Program Version=4.10
Short Identifier=Plan 01
Geom File=g01
Flow File=f01
Subcritical Flow
Calc Critical at every XS
Secant Critical Depth

--- 386_ras.f01 (steady flow) ---

Flow Title=Flow 01
Program Version=5.01
Number of Profiles= 5
Profile Names=10yr,25yr,50yr,100yr,500yr
River Rch & RM=386,34,3310.439
  611.28  780.52  944.99 1079.77 1383.03
River Rch & RM=386,34,3112.769
  615.59  786.83  952.86 1089.89 1397.84
River Rch & RM=386,34,3013.934
  626.17  802.34  972.19 1114.81 1434.44
River Rch & RM=386,34,2816.264
  631.56  810.27  982.07 1127.57 1453.22
River Rch & RM=386,34,2717.429
  635.25   815.7  988.85 1136.33 1466.13
River Rch & RM=386,34,2618.594
  640.13  822.88   997.8 1147.92 1483.22
River Rch & RM=386,34,2420.923
  646.54  832.33  1009.6  1163.2 1505.81
River Rch & RM=386,34,2322.088
  652.85  841.65 1021.23  1178.3 1528.18
River Rch & RM=386,34,2223.253
  658.69  850.28 1032.01  1192.3 1548.94
River Rch & RM=386,34,2025.583
  660.61  853.13 1035.57 1196.93 1555.83
River Rch & RM=386,34,1926.748
  668.24  864.43 1049.68  1215.3 1583.15
River Rch & RM=386,34,1827.913
  672.75  871.12 1058.05 1226.21  1599.4
River Rch & RM=386,34,1729.078
  679.07   880.5 1069.77 1241.51 1622.22
River Rch & RM=386,34,1630.243
  681.27  883.78 1073.87 1246.87 1630.23
River Rch & RM=386,34,1531.408
  683.84  887.59 1078.63 1253.09 1639.53
River Rch & RM=386,34,1432.573
  685.66   890.3 1082.02 1257.52 1646.16
River Rch & RM=386,34,1234.902
  696.43  906.35 1102.09  1283.8 1685.55
River Rch & RM=386,34,1136.067
  698.55  909.52 1106.06    1289 1693.35
River Rch & RM=386,34,1037.232
  704.17   917.9 1116.55 1302.77 1714.04
River Rch & RM=386,34,938.3972
  706.25  921.02 1120.46  1307.9 1721.76
River Rch & RM=386,34,839.5621
  712.12  929.79 1131.44 1322.34  1743.5
River Rch & RM=386,34, 740.727
  713.83  932.35 1134.65 1326.56 1749.85
River Rch & RM=386,34,641.8919
  715.19   934.4  1137.2 1329.93 1754.93
River Rch & RM=386,34,543.0569
  716.89  936.94 1140.39 1334.12 1761.26
River Rch & RM=386,34,444.2218
  719.94   941.5 1146.11 1341.65 1772.62
River Rch & RM=386,34,345.3867
  721.96  944.53  1149.9 1346.64 1780.17
River Rch & RM=386,34,246.5516
  732.91  960.97 1170.49 1373.82 1821.29
River Rch & RM=386,34,147.7165
  734.87  963.92 1174.19 1378.71  1828.7
River Rch & RM=386,34,  5.0085
  736.83  966.86 1177.88 1383.58 1836.09
Boundary for River Rch & Prof#=386,34,1
Up Type= 0
Dn Type= 2
Boundary for River Rch & Prof#=386,34,2
Up Type= 0
Dn Type= 2
Boundary for River Rch & Prof#=386,34,2
Up Type= 0
Dn Type= 2
Boundary for River Rch & Prof#=386,34,2
Up Type= 0
Dn Type= 2
Boundary for River Rch & Prof#=386,34,2
Up Type= 0
Dn Type= 2

--- 386_ras.g01 (geometry) ---

Geom Title=386
Program Version=4.10

River Reach=386,34
Reach XY= 30
1195383.59060897628293.6491938131195354.42394928628236.982544821
1195324.42395744628213.6492192681195283.59063543628187.815894769
1195194.42399451628168.6492363741195154.42400479628116.149253098
1195075.25736075628091.1492628021194897.75741231628062.815943008
1194855.25742408 628035.315952381194776.09077814 627944.48264829
1194668.59080976627941.1493190531194563.59084013627920.315994919
 1194433.5908749627797.8160350051194282.75758575627786.982709233
1194120.25763116 627699.482739921194010.25766375 627703.64940849
1193928.59102175627723.6494049251193835.25771591627722.816074505
1193769.42440147627703.6494154221193709.42441774627654.482765064
 1193535.2578005627586.9827901421193392.75784246627583.649461898
 1193178.5912402627626.1494554551193133.59125441627658.649447062
1193030.25795278 627700.316104381192921.09132158627813.649407179
1192705.25805685627986.9826953081192584.42476047628030.316019275
1192507.75811621628021.9826906291192486.09145646628042.816018387

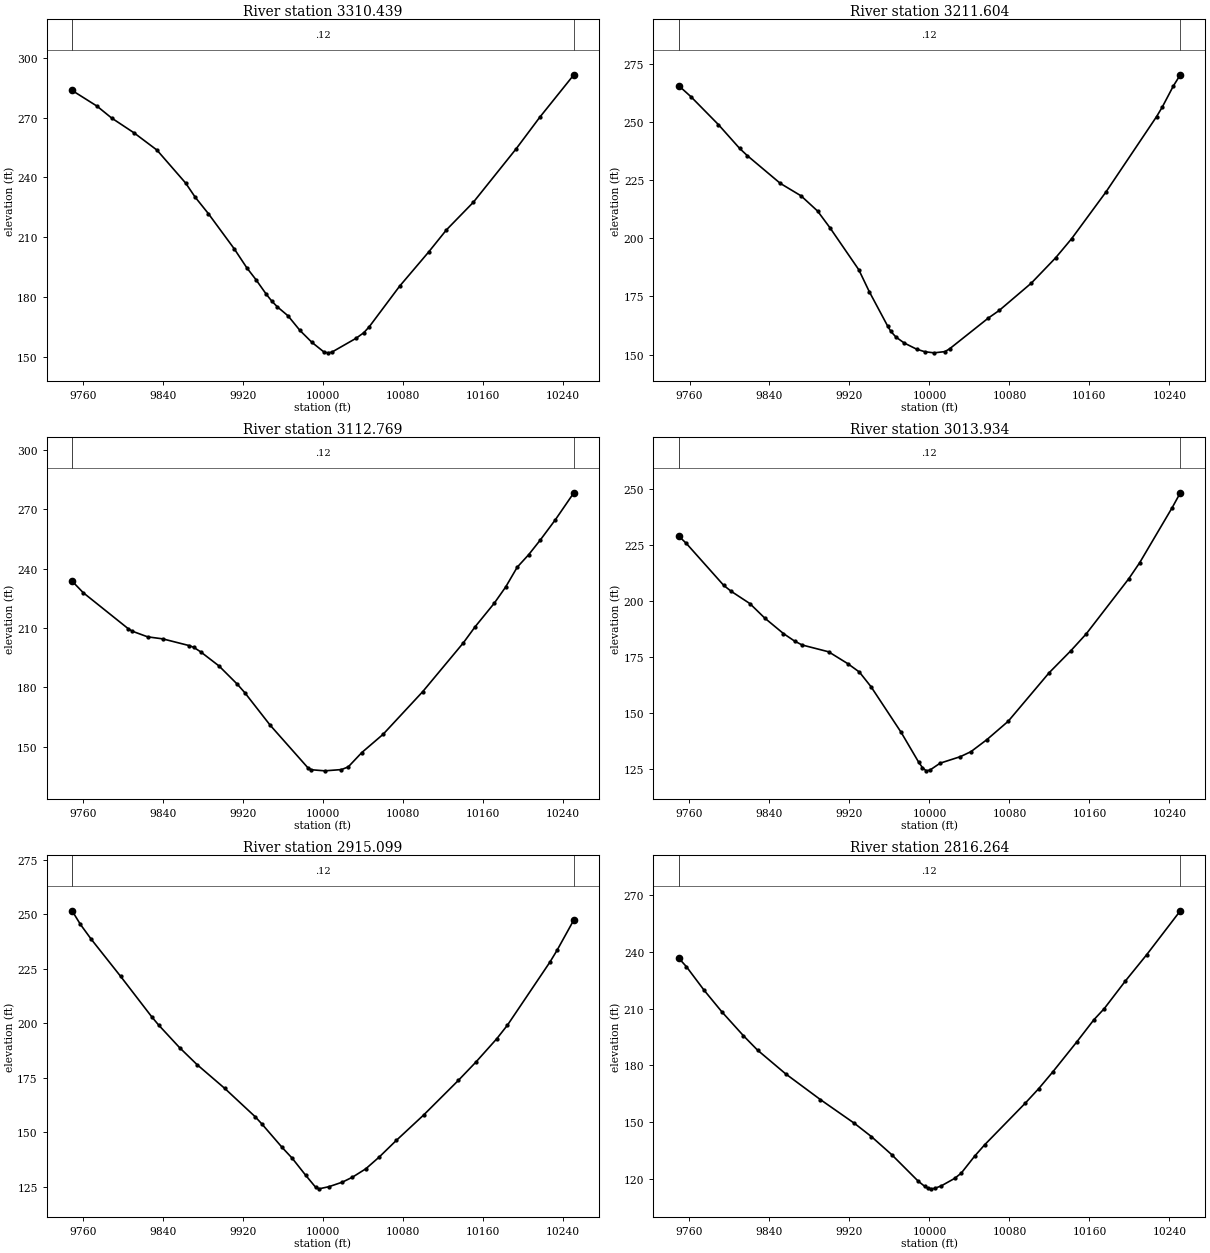
Type RM Length L Ch R = 1 ,3310.439,98.835000,98.835000,98.835000
XS GIS Cut Line= 6
1195569.89085745628126.5985766111195466.10105187628231.433741516
1195345.78551672 628319.069922961195307.14174458628352.278283693
 1195257.0922098628406.3735835681195207.18960714628469.793076677
#Sta/Elev= 30
9749.048 283.5979773.906275.75599788.523269.80749810.895262.38689833.937 253.716
9862.592237.21759872.144230.14679885.438221.83049911.379204.14949923.945194.6419
  9932.9 188.8419943.455181.38159948.732178.08419954.414175.14629965.024170.6857
9976.948163.36269988.872157.411110000.94152.564810004.79152.128810008.81152.4619
 10032.9159.365310040.78162.191510046.36165.249710076.57185.477410105.62202.6079
 10123.5213.745810150.32227.535310193.38254.466510216.97 270.25610250.92291.4383
#Mann= 3 , 0 , 0
9749.048    0.12       09749.048    0.12       010250.92    0.12       0
#XS Ineff= 2 , 0
       0                               0
Bank Sta=9749.048,10250.92
Exp/Cntr=0.3,0.1

Type RM Length L Ch R = 1 ,3211.604,98.835100,98.835100,98.835100
XS GIS Cut Line= 5
1195478.54648675628015.5624497831195326.73257947628214.177952516
1195325.50469829628215.7566569881195282.14918672628272.982575125
1195178.21922968628417.727315288
#Sta/Elev= 30
9749.009265.81369761.489 260.9689788.927248.97039810.111238.74849817.833235.6166
9850.869 223.6619871.517218.32889888.034211.79889900.423204.61319929.329186.4966
9939.772177.10779958.236 162.2259961.382159.96839966.495157.50939974.754154.9599
9987.142152.30279995.401151.1915 10004.6150.718310015.47151.247110020.13152.4328
10058.93165.7003 10069.8168.963410101.89180.718410126.13191.571710142.28199.8785
10176.57219.958810227.19252.396810232.82256.445410244.07265.659810250.99270.4337
#Mann= 3 , 0 , 0
9749.009    0.12       09749.009    0.12       010250.99    0.12       0
#XS Ineff= 2 , 0
       0                               0
Bank Sta=9749.009,10250.99
Exp/Cntr=0.3,0.1

Type RM Length L Ch R = 1 ,3112.769,98.835100,98.835100,98.835100
XS GIS Cut Line= 6
1195344.88455756627958.8699445621195252.15442202628126.484556454
1195239.63111518628161.8534072951195227.61319652628220.024837233
1195208.93685905628266.1690755661195126.94706925628407.539283156
#Sta/Elev= 30
9749.086233.71069760.252227.83949805.279209.62879809.512208.33119824.669205.5189
9839.826 204.4899866.351201.07689870.849200.18599877.591197.9767    9896190.8158
9914.408181.53799921.771177.32279947.168160.86829985.166139.18269988.509138.3203
10001.84137.770310018.52138.4119 10025.3139.7699 10038.9 147.04110060.14156.2411
10099.69177.763810140.27202.405910152.17210.6195 10171.3222.510710182.78230.7701
10194.26240.729710205.74247.073310217.22254.396210232.53264.803210250.92278.3592
#Mann= 3 , 0 , 0
9749.086    0.12       09749.086    0.12       010250.92    0.12       0
#XS Ineff= 2 , 0
       0                               0
Bank Sta=9749.086,10250.92
Exp/Cntr=0.3,0.1

Type RM Length L Ch R = 1 ,3013.934,98.835100,98.835100,98.835100
XS GIS Cut Line= 6
1195296.25881409627918.9964428821195202.55863036628085.478932778
1195177.78020982628114.2936285541195140.46422109628140.298365002
1195114.96320635628174.049869089 1195034.1593583628340.073476636
#Sta/Elev= 30
9749.058229.2548  9756.9 225.8739794.243207.14549801.712204.49129820.383199.0139
 9835.32192.51569853.992185.60499865.194182.22849872.663 180.504 9899.16177.4575
9918.416172.13459929.969168.39789941.632161.82329971.646141.50449989.078128.2453
9993.011125.70669996.784124.267810000.52 124.61610010.69127.6906   10031130.6145
10041.49 132.83410057.44138.204310078.77146.413410119.71168.093210141.43177.9344
10156.75185.427110199.36210.098510210.22217.229310242.81241.894710250.93248.5148
#Mann= 3 , 0 , 0
9749.058    0.12       09749.058    0.12       010250.93    0.12       0
#XS Ineff= 2 , 0
       0                               0
Bank Sta=9749.058,10250.93
Exp/Cntr=0.3,0.1

Type RM Length L Ch R = 1 ,2915.099,98.835100,98.835100,98.835100
XS GIS Cut Line= 6
1195148.84341328627852.5660562381195098.67134759627978.693195857
1195083.65606193628031.7076442841195052.18540263  628176.2114131
1195030.79243967628239.3719044371194994.40708191628328.660937543
#Sta/Elev= 30
9749.039251.70669757.419245.43659768.126238.69529797.511221.66149828.559203.1368
 9835.55199.30219856.525188.90869874.003181.11429901.548170.26089932.237157.1523
9939.057153.7682 9959.17143.06559969.219138.12479982.617130.34889992.665124.7915
9996.015124.066210006.04125.060910019.42127.145910029.46129.403110042.84133.2607
10056.35138.703610073.29146.261210100.68157.942910135.32173.799110152.64182.0895
10173.85192.970510184.48199.171110226.99228.132710234.08233.512410250.96247.5218
#Mann= 3 , 0 , 0
9749.039    0.12       09749.039    0.12       010250.96    0.12       0
#XS Ineff= 2 , 0
       0                               0
Bank Sta=9749.039,10250.96
Exp/Cntr=0.3,0.1

Type RM Length L Ch R = 1 ,2816.264,98.835100,98.835100,98.835100
XS GIS Cut Line= 6
 1195048.7854957627846.495585311 1194992.5147492627990.444865167
1194980.19402583 628039.683809271194954.96031056628179.449815545
1194932.48161277628249.6476422691194902.95628421628324.756025032
#Sta/Elev= 30
9749.054236.91699756.876232.32589774.669219.78969792.462208.34219813.813195.8295
9828.048188.13049856.212175.55049890.872161.96269925.055149.33599941.965142.3433
9962.115132.86459988.682118.80569995.323116.00239998.644114.995710001.95114.6937
10005.27 114.92410011.91116.286410025.18120.207510031.82 123.00710045.14131.9408
10055.22137.997110095.57159.878210109.33167.746210123.11176.413710147.32192.4214
10164.45 204.16910174.89 210.10810196.04224.739210217.19238.540910250.95261.8709
#Mann= 3 , 0 , 0
9749.054    0.12       09749.054    0.12       010250.95    0.12       0
#XS Ineff= 2 , 0
       0                               0
Bank Sta=9749.054,10250.95
Exp/Cntr=0.3,0.1

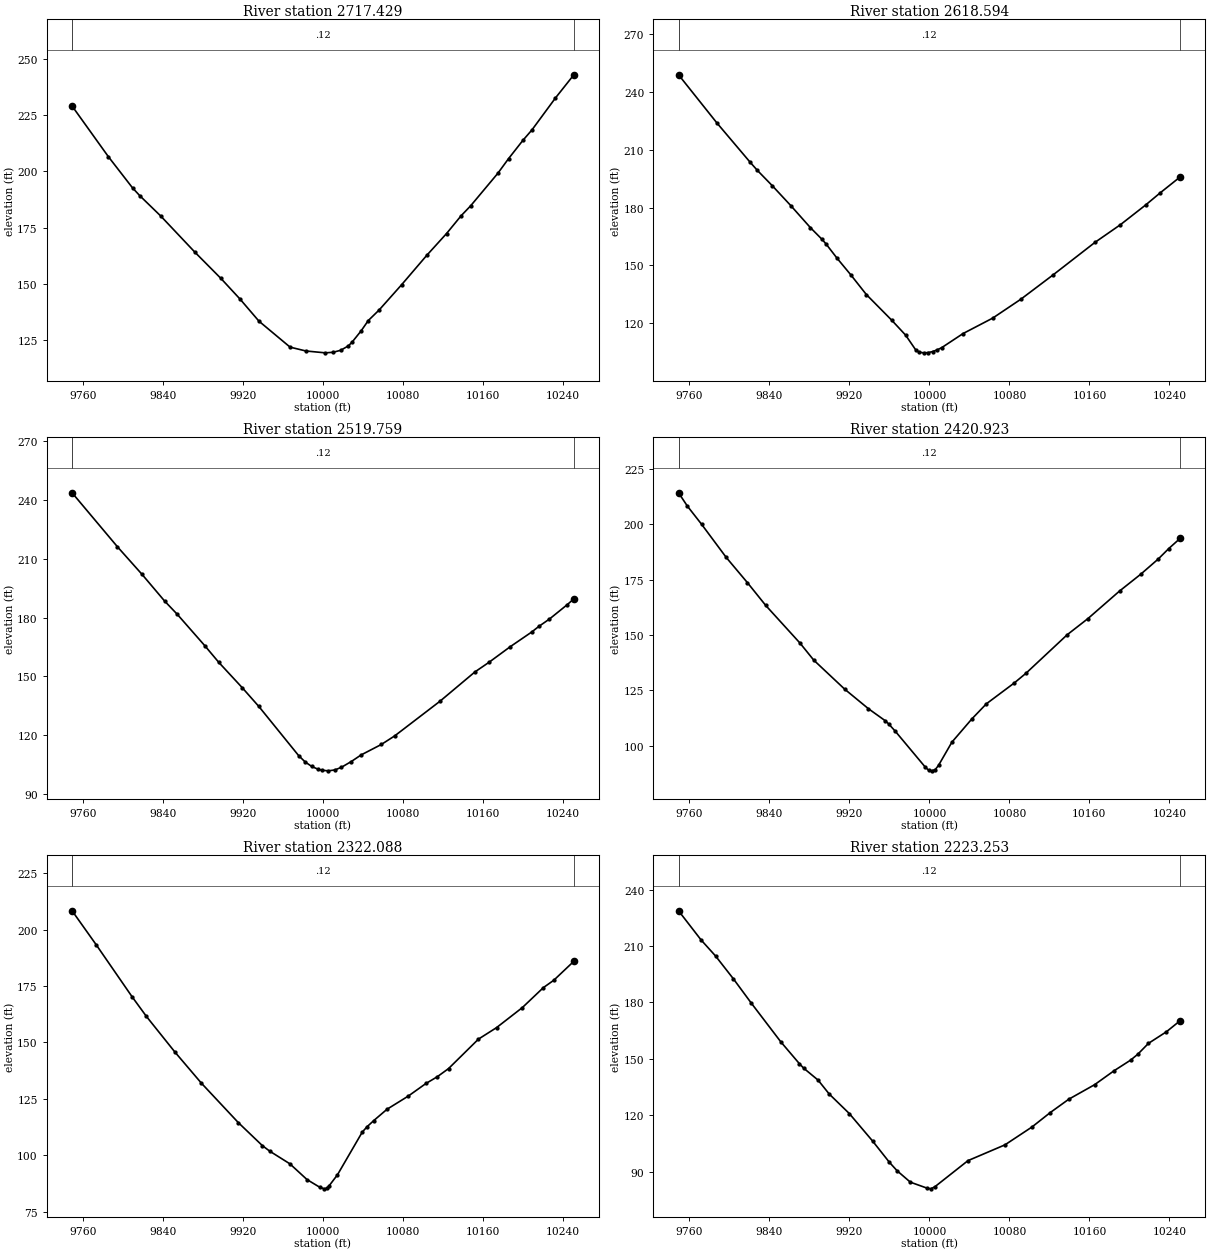
Type RM Length L Ch R = 1 ,2717.429,98.835100,98.835100,98.835100
XS GIS Cut Line= 6
1195001.09627187627831.9447493591194962.93886353627911.844517413
1194936.42889556627962.4896234411194856.90589725628090.418029156
1194827.07852374628142.7588322731194764.54622352628273.965709845
#Sta/Elev= 30
9749.013229.21869785.425  206.559809.488 192.6879816.759189.19179837.556 180.197
9871.921163.9689 9897.93152.26679916.964143.09429935.998133.18629967.112121.6104
9982.881119.899510002.21119.067310009.95119.3039 10017.7120.202810025.44122.1778
10029.31 123.93910038.16128.868110045.37133.497510056.14138.167610078.79149.5174
10103.91162.618610123.59 172.29110138.26180.271710147.66184.643110174.87199.1528
10185.69205.754410200.13213.965310209.06218.5499 10232.6232.823410250.98243.1562
#Mann= 3 , 0 , 0
9749.013    0.12       09749.013    0.12       010250.98    0.12       0
#XS Ineff= 2 , 0
       0                               0
Bank Sta=9749.013,10250.98
Exp/Cntr=0.3,0.1

Type RM Length L Ch R = 1 ,2618.594,98.835100,98.835100,98.835100
XS GIS Cut Line= 6
1194950.57982094627773.2842845891194872.38557012627917.231573798
1194841.31611094627955.3410212271194783.99644581628010.070215488
1194756.58483341628047.373389618 1194684.3697612 628193.51162681
#Sta/Elev= 30
9749.107248.82419787.661223.73819820.667203.52369828.001199.2416 9842.67  191.43
9861.632180.8658 9880.88169.64839892.429163.61639896.278161.36189907.827153.6132
9921.128145.28979936.936134.9138 9962.24121.6463 9976.16113.90029986.212 106.288
9989.711105.06129994.228104.70969998.745104.838910003.21105.377810007.77106.2474
10012.34107.422210033.66 114.71610063.24 122.70110091.41132.497810123.81145.1667
10165.71162.031710191.01171.1314 10216.3181.381110230.75 187.62310250.88195.9547
#Mann= 3 , 0 , 0
9749.107    0.12       09749.107    0.12       010250.88    0.12       0
#XS Ineff= 2 , 0
       0                               0
Bank Sta=9749.107,10250.88
Exp/Cntr=0.3,0.1

Type RM Length L Ch R = 1 ,2519.759,98.835100,98.835100,98.835100
XS GIS Cut Line= 6
1194795.74378282627699.8043435561194740.60021008627855.292585453
1194731.75362995627905.9947521121194728.71055278627974.741440628
1194720.70522307628012.1594784531194655.93795871628178.086672499
#Sta/Elev= 30
9749.094243.56769794.522216.02589819.155 201.9469841.576188.44529854.241 181.683
 9881.67165.75529895.916157.11299919.235144.28049935.887134.69229975.708109.6412
9982.275106.39859988.842104.1117 9995.41102.65319998.693102.218410005.26101.9001
10011.83102.3501 10018.4103.686810028.26106.621610038.19110.011110058.32115.3212
10071.74119.705110116.93137.322610151.96152.288810166.16157.237410187.47165.2125
10208.77172.629510215.87175.476210226.52179.245310244.27186.547710250.91189.5369
#Mann= 3 , 0 , 0
9749.094    0.12       09749.094    0.12       010250.91    0.12       0
#XS Ineff= 2 , 0
       0                               0
Bank Sta=9749.094,10250.91
Exp/Cntr=0.3,0.1

Type RM Length L Ch R = 1 ,2420.923,98.835000,98.835000,98.835000
XS GIS Cut Line= 6
1194706.90521525627697.8187049161194652.38329733627842.443164494
 1194640.6894574627887.2789763691194623.92616391627981.405205532
1194611.91177562628030.9362263161194559.53349823628176.149014619
#Sta/Elev= 30
9749.035  214.28 9757.92208.22979772.052200.07149796.783185.04099817.981173.6406
9836.296163.34769870.398146.41519884.295138.64719915.275125.50719939.009116.6839
 9955.86111.24159959.194109.8313 9965.86106.50529995.85990.283529999.19288.90394
10002.5288.6155710005.8689.1923410009.1991.1563710022.51101.5923 10042.5112.1057
10057.01118.922110084.84128.318510096.48132.674710137.85150.1344 10158.6157.4391
10190.23169.895210211.32177.4547 10228.9184.350410239.44189.088810250.97193.7524
#Mann= 3 , 0 , 0
9749.035    0.12       09749.035    0.12       010250.97    0.12       0
#XS Ineff= 2 , 0
       0                               0
Bank Sta=9749.035,10250.97
Exp/Cntr=0.3,0.1

Type RM Length L Ch R = 1 ,2322.088,98.835100,98.835100,98.835100
XS GIS Cut Line= 6
1194664.08571715627684.206244194 1194593.2705845627831.370201512
1194566.20905219627873.0909925821194519.00351282627927.833608226
1194488.51108731627971.6114338771194416.01064206628117.575930869
#Sta/Elev= 30
9749.079 208.2879773.058193.35079809.039170.28219823.432161.53989851.847145.8162
9878.471131.97299915.337114.54689939.453104.33969946.905101.86539966.88496.31684
9984.08889.32401 9996.9985.8887610001.4285.2369610003.7485.4591510005.7786.36381
10014.4891.43206 10039.3110.3381 10044.1112.718110050.78115.435710064.09120.4646
10085.23126.258710103.06131.878610114.31134.835710125.56138.441610155.54 151.507
10173.58156.569810199.35165.4275 10220.5174.309510230.84177.537410250.92185.9454
#Mann= 3 , 0 , 0
9749.079    0.12       09749.079    0.12       010250.92    0.12       0
#XS Ineff= 2 , 0
       0                               0
Bank Sta=9749.079,10250.92
Exp/Cntr=0.3,0.1

Type RM Length L Ch R = 1 ,2223.253,98.835100,98.835100,98.835100
XS GIS Cut Line= 6
1194599.49568111627613.244999454 1194564.4122684627691.626006429
1194531.02027412627753.5503840531194440.35213907627872.469198469
1194417.84701804627907.4557205181194351.65763316628046.892859884
#Sta/Elev= 30
9749.061228.73229771.682213.1915 9786.06204.72449804.032 192.4969822.005179.5382
9851.346159.08849869.983147.44779874.207145.0994 9888.62138.75259899.803131.3345
9919.848120.9897 9943.15106.37479959.98495.05651 9967.7190.552029980.94584.50353
9997.16381.4245710001.3680.9677610005.5782.1277710038.5495.9509110075.53104.3379
10102.49 113.80110120.93121.527110139.37128.591410165.19136.308210184.64 143.712
10201.15149.343710208.32152.462910219.08158.278210237.02164.428810250.94170.4061
#Mann= 3 , 0 , 0
9749.061    0.12       09749.061    0.12       010250.94    0.12       0
#XS Ineff= 2 , 0
       0                               0
Bank Sta=9749.061,10250.94
Exp/Cntr=0.3,0.1

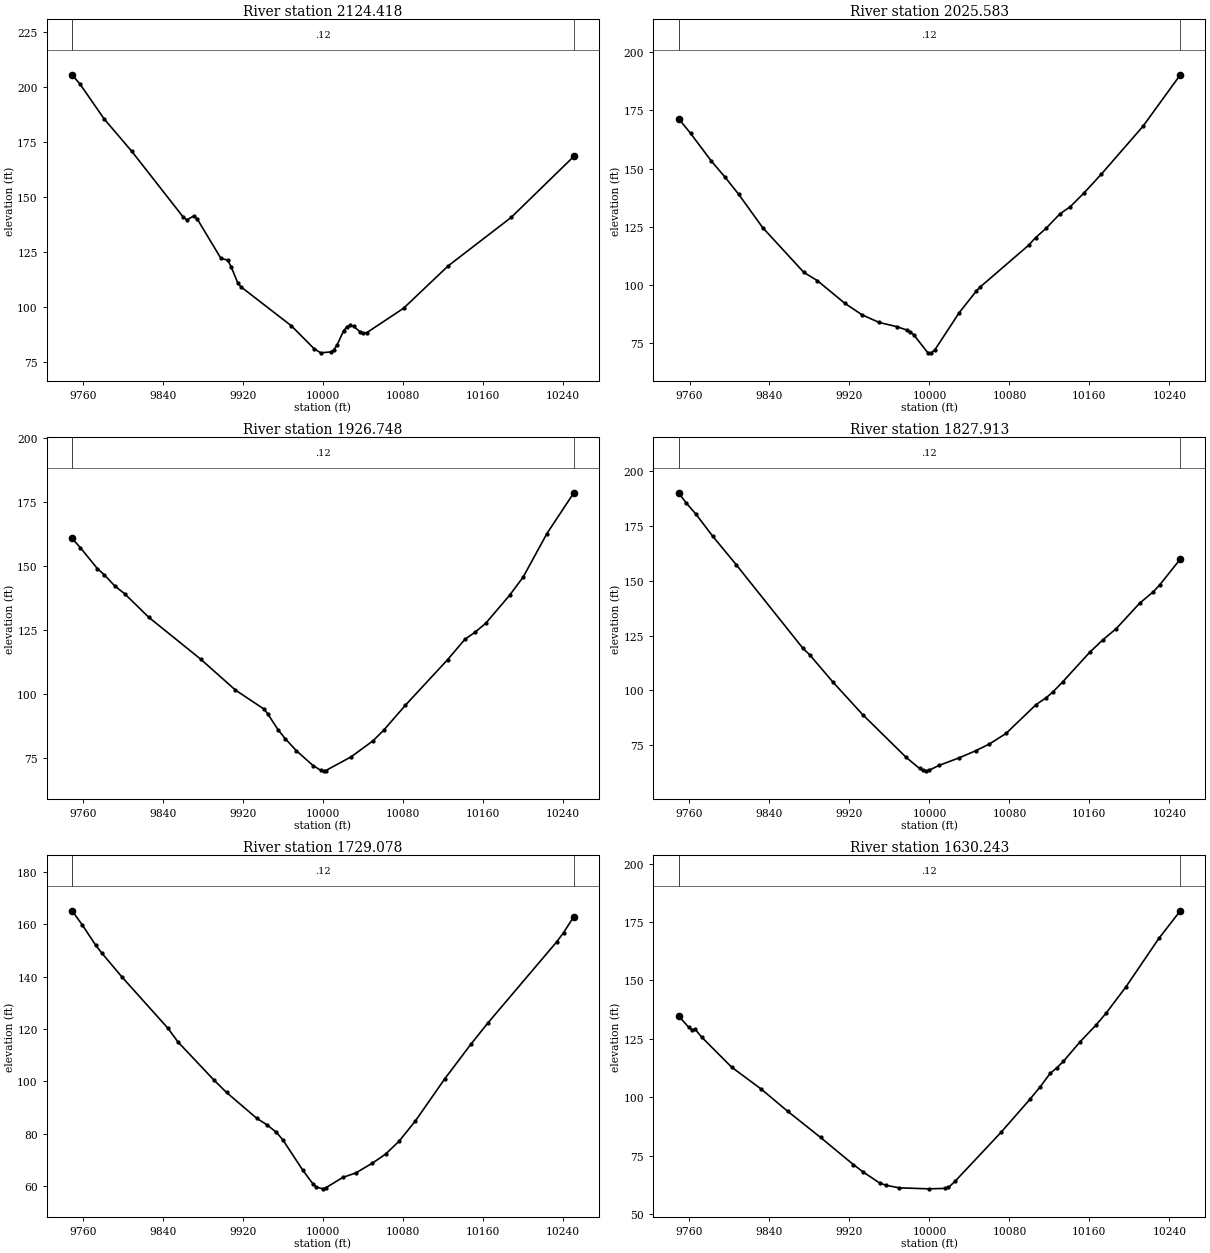
Type RM Length L Ch R = 1 ,2124.418,98.835100,98.835100,98.835100
XS GIS Cut Line= 6
1194447.48835431627547.6603066071194396.99188339627712.120083707
1194389.89128471627756.0921641321194385.07793295627835.826646949
1194376.71234785627877.242029081 1194319.9620719628030.108709532
#Sta/Elev= 30
9749.047205.4218 9756.93201.23069781.096185.37079808.714170.63419860.498140.5578
9863.931139.47079870.724141.21199874.121139.92959897.897121.9482 9904.69121.1297
9908.086118.18189914.879  110.679918.276108.87449968.16191.353589991.18180.83045
9997.75878.9767910007.6279.40087 10010.980.2877510014.1982.6722510020.7689.07768
10024.04 90.878310027.3391.4273210030.6290.9910210037.1988.5440810040.4787.86274
10043.7688.1359110080.5499.2161510125.22118.515110188.35140.600510250.93168.3299
#Mann= 3 , 0 , 0
9749.047    0.12       09749.047    0.12       010250.93    0.12       0
#XS Ineff= 2 , 0
       0                               0
Bank Sta=9749.047,10250.93
Exp/Cntr=0.3,0.1

Type RM Length L Ch R = 1 ,2025.583,98.835100,98.835100,98.835100
XS GIS Cut Line= 6
1194366.66088592627550.2038646051194306.49357986627746.612866566
1194291.89422372 627788.72881888 1194291.3097867627790.641522038
1194249.05667696627910.5630180861194210.09355669628027.064406671
#Sta/Elev= 30
9749.007171.46039761.045165.10519781.633153.30759795.358146.38479809.083138.9981
9833.103 124.6849874.279105.47379888.004101.83899915.45492.131999932.61187.20067
9949.76883.937279967.07482.172759977.491 80.68529980.96379.878399984.43678.58696
9998.32570.9883510001.7770.9020310005.3472.12548 10029.688.02369   1004797.47767
10050.4799.0487410099.17 117.05610106.13120.311710116.57 124.29510130.47130.5051
10140.85133.604510154.64139.509510171.98147.594310213.49168.053510250.99 190.232
#Mann= 3 , 0 , 0
9749.007    0.12       09749.007    0.12       010250.99    0.12       0
#XS Ineff= 2 , 0
       0                               0
Bank Sta=9749.007,10250.99
Exp/Cntr=0.3,0.1

Type RM Length L Ch R = 1 ,1926.748,98.835100,98.835100,98.835100
XS GIS Cut Line= 6
1194292.83700886627504.5821168551194263.56215916 627602.74156919
 1194242.7894129627661.1981768721194177.65478379627799.346463407
1194158.75655779627846.0111521841194120.62490643627974.811920091
#Sta/Elev= 30
9749.025160.71499757.289157.13099774.407148.91229781.255146.52459791.525142.2653
9801.796139.06369825.762129.92679877.552113.63449912.371101.55159940.95294.12609
9944.52892.382529955.25885.943369962.41682.495269973.37177.862599990.14872.04655
 9997.6270.24148   1000170.0009610002.5970.0619910028.1675.4650310050.0881.72767
10061.0485.9876110082.4495.6029210124.71113.412610141.97 121.35210152.32124.1657
10162.68  127.5410186.61138.498310200.22145.622910224.04162.624110250.97178.5423
#Mann= 3 , 0 , 0
9749.025    0.12       09749.025    0.12       010250.97    0.12       0
#XS Ineff= 2 , 0
       0                               0
Bank Sta=9749.025,10250.97
Exp/Cntr=0.3,0.1

Type RM Length L Ch R = 1 ,1827.913,98.835100,98.835100,98.835100
XS GIS Cut Line= 6
1194162.28054805627452.6988016681194122.11190429627662.789350147
1194116.91691119627698.4827400141194116.91691125627700.482740014
1194115.05742259 627714.546835371194070.80609921627946.150359919
#Sta/Elev= 30
9749.034190.16419756.476185.66869766.497180.39159783.198170.3592 9806.58157.4369
9873.385 119.2499880.065116.31689903.447103.8071 9933.5188.815139976.829 69.4106
 9990.0964.372739993.40663.531049996.72163.2951310000.0363.6640410009.9565.84422
10029.9469.2550910046.6472.53064   1006075.54706 10076.780.3719210106.7693.55626
10116.7896.6326710123.4699.2775110133.48103.9568 10160.2117.322710173.57123.1168
10186.93128.206210210.31139.778410223.67144.890510230.35 148.12410250.98159.9187
#Mann= 3 , 0 , 0
9749.034    0.12       09749.034    0.12       010250.98    0.12       0
#XS Ineff= 2 , 0
       0                               0
Bank Sta=9749.034,10250.98
Exp/Cntr=0.3,0.1

Type RM Length L Ch R = 1 ,1729.078,98.835100,98.835100,98.835100
XS GIS Cut Line= 6
1194021.05504802627453.0652146461194011.87155456627534.941488032
 1194009.3193329627606.9611215721194027.47313915627768.579808724
1194029.50135749627818.8751124231194017.11690685627952.571151432
#Sta/Elev= 30
9749.062165.1725 9759.35159.74269772.555152.10029779.158148.87229798.967139.8865
9845.109120.24859854.958115.0851 9891.07100.48429903.51795.803399933.78885.91531
 9943.6583.520749953.51280.56473 9960.1277.559439979.96266.016979989.883 60.9163
 9993.1959.68007  9999.8 58.986210003.1159.4453710019.6863.3210510032.9365.07806
 10049.568.8098510062.7672.2947710075.9277.0996510092.3484.8603710121.89101.0496
10148.17 114.324 10164.6122.175810233.97153.395710240.58 156.79310250.93162.9642
#Mann= 3 , 0 , 0
9749.062    0.12       09749.062    0.12       010250.93    0.12       0
#XS Ineff= 2 , 0
       0                               0
Bank Sta=9749.062,10250.93
Exp/Cntr=0.3,0.1

Type RM Length L Ch R = 1 ,1630.243,98.835100,98.835100,98.835100
XS GIS Cut Line= 6
1193937.28735456627472.9225108431193928.32865326627544.033819091
1193923.99830172627596.8916930481193921.13262762627839.714329163
1193916.15293187627910.1194878121193908.59438002627973.448544404
#Sta/Elev= 30
9749.049134.90469759.179129.97469762.486128.91579765.793 129.0399772.406125.6793
9802.167112.91179831.878103.48159858.212 94.03999891.07382.845649923.88471.24342
9933.72768.056159950.13263.369819956.69462.358289969.81861.279579999.34960.84966
10015.7661.0397510019.0461.43175 10025.664.0653910071.5484.9872810101.0799.43156
10110.91104.587210120.76110.233110127.34112.582310133.92115.354710150.36123.6105
10166.81 131.01410176.68135.988410196.45147.197210229.49168.000710250.96179.8192
#Mann= 3 , 0 , 0
9749.049    0.12       09749.049    0.12       010250.96    0.12       0
#XS Ineff= 2 , 0
       0                               0
Bank Sta=9749.049,10250.96
Exp/Cntr=0.3,0.1

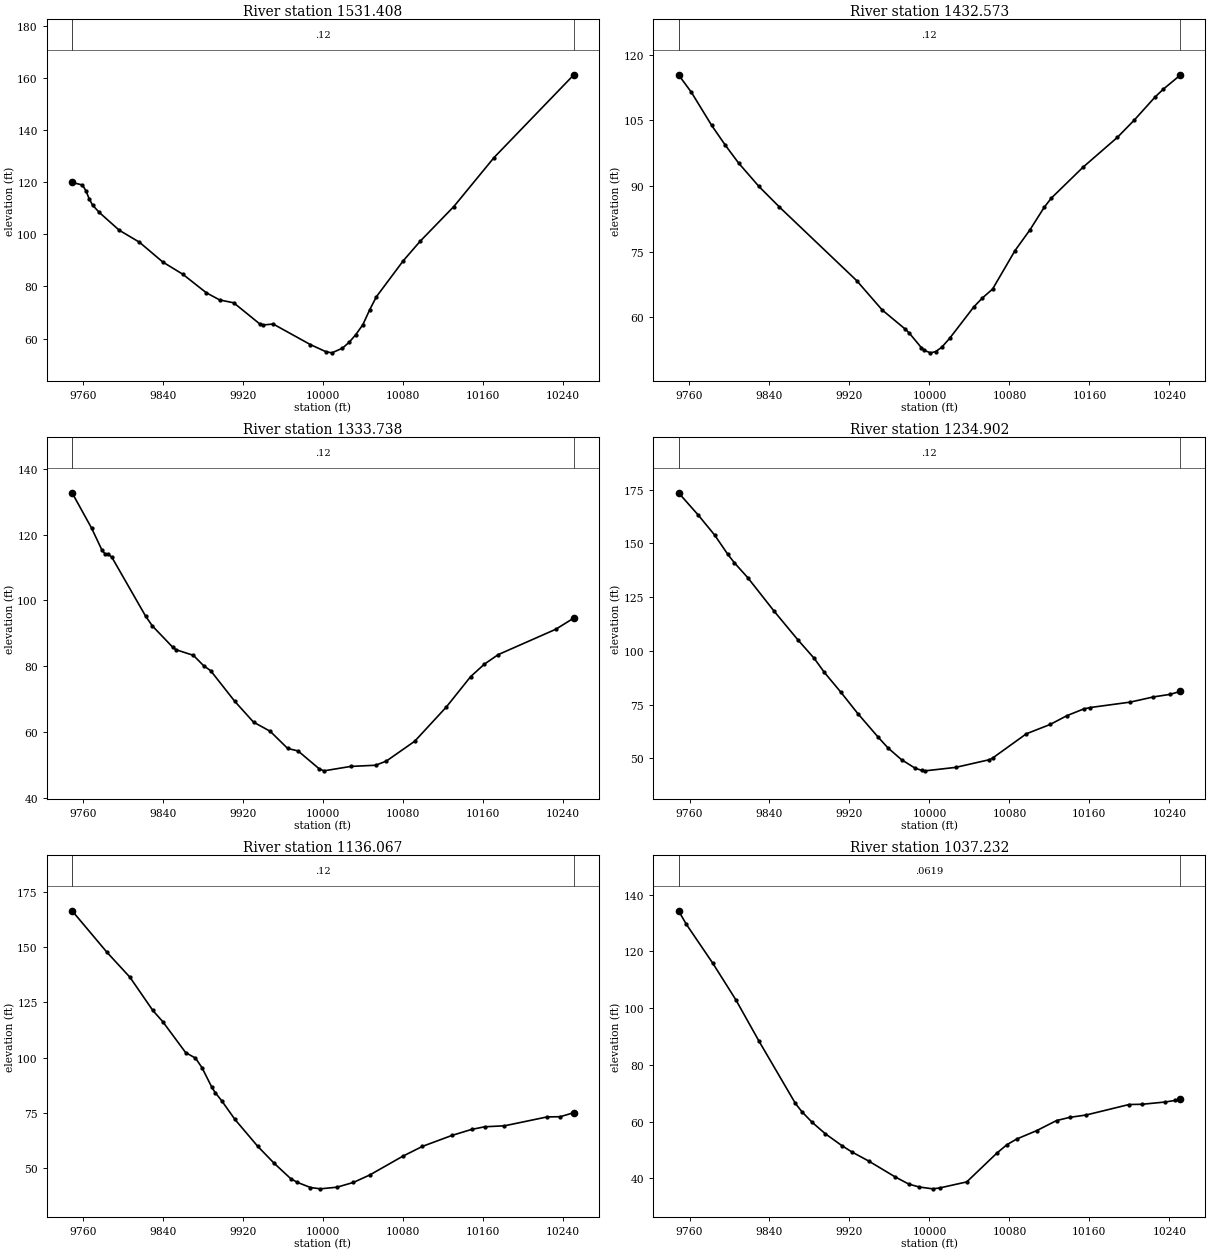
Type RM Length L Ch R = 1 ,1531.408,98.835000,98.835000,98.835000
XS GIS Cut Line= 6
1193878.85556329627472.7538535121193836.14509537627684.996606039
1193830.84744104627704.8731186131193819.45358267 627730.22940021
1193811.77756691627756.577188039 1193767.8220133627961.524725724
#Sta/Elev= 30
9749.033119.88479759.458118.88779762.804116.73239766.151 113.6259769.498   111.2
9776.191108.3917 9796.27101.5294 9816.3596.971529839.77689.357019859.85684.64984
9883.28277.571669896.66974.813059910.73473.709039936.828  65.5979940.17465.21563
9950.21465.570479987.407 57.685210002.8854.96842   1000954.52103 10019.5 56.3147
10026.3358.6176710032.8861.51633   1004065.3815910046.7571.0482110053.4876.05568
10080.3989.87045 10097.297.3161910130.84110.607710171.12129.422910250.97161.1705
#Mann= 3 , 0 , 0
9749.033    0.12       09749.033    0.12       010250.97    0.12       0
#XS Ineff= 2 , 0
       0                               0
Bank Sta=9749.033,10250.97
Exp/Cntr=0.3,0.1

Type RM Length L Ch R = 1 ,1432.573,98.835100,98.835100,98.835100
XS GIS Cut Line= 6
1193828.09711749627444.2444879851193783.00378234627600.795898672
1193760.75271628 627645.552076241193688.08792979627758.257481356
1193660.83739263627826.7239010931193638.94950931627904.379735484
#Sta/Elev= 30
9749.089115.46679761.936111.45859782.195103.89019795.70199.399949809.20795.24562
9829.46689.904459849.982 85.1877 9927.1768.354079952.81761.602929975.96557.20702
9979.96656.296379991.97152.974039994.98352.35905   1000151.80228 10006.252.08183
10012.1953.0523210020.3155.1488410044.4362.3306710052.7964.3242510063.1566.40171
10085.6275.2229410100.4279.9227510114.7485.10848 10121.987.2297810153.5294.28467
10188.04101.151910205.08105.145810225.53110.344310233.97112.186110250.91115.3972
#Mann= 3 , 0 , 0
9749.089    0.12       09749.089    0.12       010250.91    0.12       0
#XS Ineff= 2 , 0
       0                               0
Bank Sta=9749.089,10250.91
Exp/Cntr=0.3,0.1

Type RM Length L Ch R = 1 ,1333.738,98.835100,98.835100,98.835100
XS GIS Cut Line= 6
1193726.84251281627391.7401212971193713.82450334627449.379570874
1193694.91326068627515.7262327371193600.15929477627761.859169933
1193586.31239707627806.0445337211193571.25500041627868.009743128
#Sta/Elev= 30
9749.037132.72179768.572121.96449778.662115.45739782.026114.10669785.389114.0055
9788.753113.15899822.59195.209759829.41492.207139849.88385.711679853.29584.96216
9870.35283.292749880.67680.129739887.67378.614069911.65269.346239930.53562.97462
9947.15460.203679964.64854.982819975.14554.201049996.13848.80347   1000148.16084
10027.8449.5047410052.71 49.862610063.3651.1238310091.7857.1582410123.3767.56194
10147.7676.8254510161.5180.6174510175.2783.4967710232.8891.2148510250.9794.63242
#Mann= 3 , 0 , 0
9749.037    0.12       09749.037    0.12       010250.97    0.12       0
#XS Ineff= 2 , 0
       0                               0
Bank Sta=9749.037,10250.97
Exp/Cntr=0.3,0.1

Type RM Length L Ch R = 1 ,1234.902,98.835100,98.835100,98.835100
XS GIS Cut Line= 6
1193607.59814977627345.5573389841193597.62359225627418.057944064
 1193584.5331645627491.9371019661193531.14567797627716.610687185
1193519.78103157627774.5315247271193510.19464196627837.583274924
#Sta/Elev= 30
9749.015173.50469768.503163.27129785.062153.89459798.309144.88399804.932140.9197
9818.179 134.088 9844.81118.35639868.134105.27149884.79396.487739894.78990.04757
9911.55980.689279928.34970.847889948.496 59.99719958.59254.853179972.10749.38944
9985.62145.478129992.37944.403159995.75744.2196510026.1345.8178710059.9149.39074
10063.2950.1878910096.95  61.444 10120.765.7686310137.4969.8589210154.2172.97358
 10160.973.6598810200.9176.1757410224.14 78.596410240.7479.7786410250.9881.16844
#Mann= 3 , 0 , 0
9749.015    0.12       09749.015    0.12       010250.98    0.12       0
#XS Ineff= 2 , 0
       0                               0
Bank Sta=9749.015,10250.98
Exp/Cntr=0.3,0.1

Type RM Length L Ch R = 1 ,1136.067,98.835100,98.835100,98.835100
XS GIS Cut Line= 6
1193473.66471945627333.2938098051193469.70248684627514.003855475
1193466.97739538627557.9903485881193460.54186229 627605.50685443
1193457.90782576627638.5413421751193451.98051708627834.506792208
#Sta/Elev= 30
9749.018166.44439783.876147.69129806.848136.40359829.819121.33649839.664116.3245
9862.635102.2853 9872.48 99.77889879.04495.424819888.88886.54641 9892.17 84.2032
9898.73380.48045 9911.8672.08607 9934.84 59.82969951.27552.161029967.71145.26816
9974.28843.585879987.51941.237779997.443 40.636810014.0141.3799210030.5243.54689
10046.9846.9411610079.8255.3873710099.5259.8463810129.0664.8078910148.7567.52589
10161.8868.7178210181.5869.1561410224.2573.1750810237.3773.2716610250.9975.11252
#Mann= 3 , 0 , 0
9749.018    0.12       09749.018    0.12       010250.99    0.12       0
#XS Ineff= 2 , 0
       0                               0
Bank Sta=9749.018,10250.99
Exp/Cntr=0.3,0.1

Type RM Length L Ch R = 1 ,1037.232,98.835100,98.835100,98.835100
XS GIS Cut Line= 6
 1193324.8922058627344.0473893781193349.70257683 627522.44675714
1193376.25383718627627.7991365261193384.34624343627669.136809805
1193392.11060723627729.5668607141193401.77462864627839.230643824
#Sta/Elev= 30
9749.016134.28819756.772129.56229783.234115.83359806.389102.89429829.54388.33243
9865.963 66.39429872.60363.426589882.56359.789759895.84355.733129912.443 51.5385
9922.40349.316159939.10746.14066 9965.95 40.4761 9979.4937.971539989.70436.97116
10003.3336.3195410010.1336.6241210037.3538.7638510067.4548.9108310077.4851.86257
10087.4353.8907210107.2756.8270310127.1260.3699710140.3561.5045810156.8262.33847
10199.6466.0245110212.8166.1167510235.8766.9140610245.7567.4725210250.9868.11865
#Mann= 3 , 0 , 0
9749.016  0.0619       09749.016  0.0619       010250.98  0.0619       0
#XS Ineff= 2 , 0
       0                               0
Bank Sta=9749.016,10250.98
Exp/Cntr=0.3,0.1

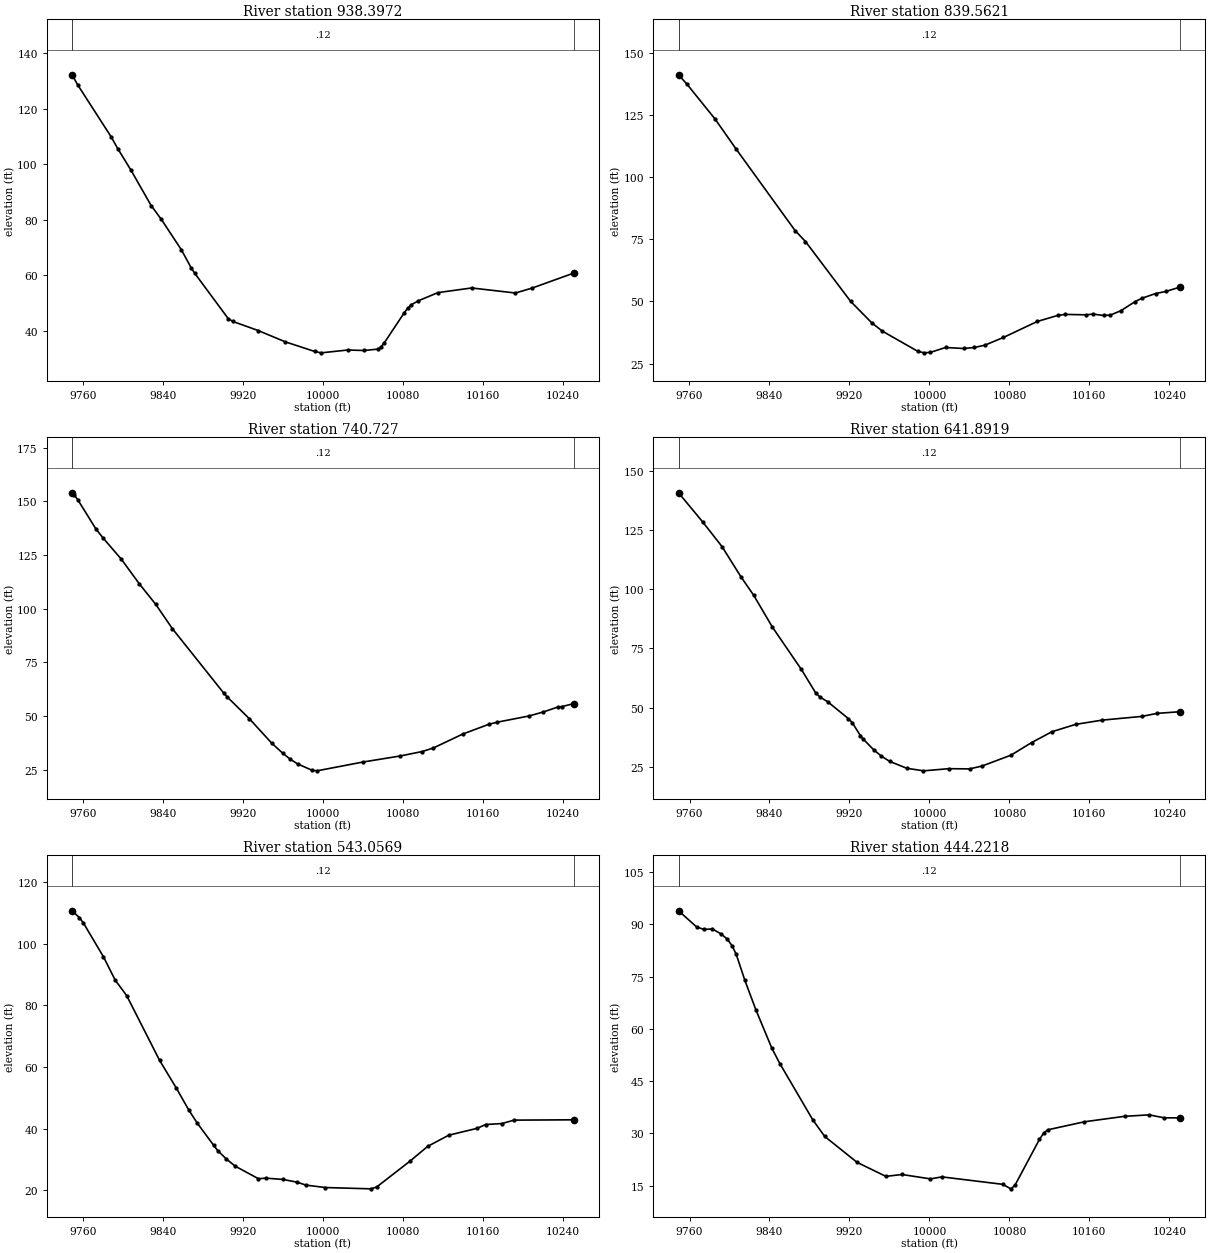
Type RM Length L Ch R = 1 ,938.3972,98.835100,98.835100,98.835100
XS GIS Cut Line= 6
1193224.15031304627366.0471852441193262.53452104627553.624594688
1193267.89290773627588.8683565841193273.20704577627641.150655585
1193279.34531355 627678.228700321193320.87226202627858.221639158
#Sta/Elev= 30
9749.012132.17999754.502128.6193 9787.99109.88439794.687105.59829808.08397.70779
9828.17685.022779838.22280.122819858.315  69.1439868.36162.47726 9871.7160.64807
9905.19844.327759909.90343.287079935.33840.002949961.93336.000889991.69932.47709
9998.29331.9860110024.6833.0012110041.2732.8348410054.5733.31604 10057.934.08448
10061.23 35.528510081.3646.4578910084.7348.06196 10088.1 49.265710095.5650.76608
10115.0453.6848910148.7155.3617210192.4853.5469910209.3155.3299610250.9860.73945
#Mann= 3 , 0 , 0
9749.012    0.12       09749.012    0.12       010250.98    0.12       0
#XS Ineff= 2 , 0
       0                               0
Bank Sta=9749.012,10250.98
Exp/Cntr=0.3,0.1

Type RM Length L Ch R = 1 ,839.5621,98.835100,98.835100,98.835100
XS GIS Cut Line= 6
1193083.99152019 627396.022235331193145.69264419627571.214905835
1193161.77445908627609.5932166681193180.18622998627639.618521209
1193193.95678499627670.5895086421193263.41822514627863.891727482
#Sta/Elev= 30
9749.066141.27289757.772137.36089785.599123.45829806.469111.47789865.60178.57052
9876.03674.143469921.25550.006359942.29141.417289952.96338.048579988.348 29.9279
9994.81929.3133210000.9729.4991510016.1631.4648510034.1131.0678910044.8931.46461
10055.4132.3943510074.0335.5101510107.9341.9528110128.9444.4451210135.8944.78697
10156.7544.61278 10163.7 44.915610174.1344.3634510181.0844.5274210191.5146.27258
10205.4149.8653410212.3751.2619210226.2753.19853 10236.754.0413610250.97 55.8389
#Mann= 3 , 0 , 0
9749.066    0.12       09749.066    0.12       010250.97    0.12       0
#XS Ineff= 2 , 0
       0                               0
Bank Sta=9749.066,10250.97
Exp/Cntr=0.3,0.1

Type RM Length L Ch R = 1 , 740.727,98.835100,98.835100,98.835100
XS GIS Cut Line= 6
1192974.80183809627451.4121189011193056.38997579627619.260449204
 1193075.4890597627654.9410196321193111.70512051627714.146915129
1193169.28813017627824.7654665621193204.19994452627897.528534055
#Sta/Elev= 30
9749.016153.99139751.261152.96619754.883150.60889772.993137.05089780.237132.8074
9798.346123.02929816.456111.47449832.804101.96349849.28990.731999900.65560.73098
9904.32458.840249926.339 48.75289948.534 37.44929959.69832.68725 9967.1429.93459
9974.58327.689319989.16624.712179993.99224.4565610040.0728.5656510077.1531.37191
10099.3533.4579110110.44 35.103210140.0341.6343410165.9246.1308610174.4847.13347
10206.02  50.00410220.5851.9021910235.13 54.211210238.7754.3610810250.9955.77414
#Mann= 3 , 0 , 0
9749.016    0.12       09749.016    0.12       010250.99    0.12       0
#XS Ineff= 2 , 0
       0                               0
Bank Sta=9749.016,10250.99
Exp/Cntr=0.3,0.1

Type RM Length L Ch R = 1 ,641.8919,98.835000,98.835000,98.835000
XS GIS Cut Line= 6
1192863.25674503627517.8091598591192896.80610943627574.254387608
1192934.10222804627630.7589836211193077.32919707627816.037911733
1193116.68668124 627874.627031671193149.14735575627929.522090005
#Sta/Elev= 30
9749.024140.70499773.382128.30659792.465 118.0289811.548105.18579824.25297.42723
9842.90284.030619871.89766.146769886.27456.224779890.34154.569369898.476 52.4416
9918.81245.44082 9922.8843.656739931.01438.173549933.55536.871629944.05332.33476
9952.01229.537159960.41827.31693 9977.2324.470129994.042  23.36810019.16 24.2754
10040.1724.1882310052.7725.4163710081.6729.9978110102.1835.2974810122.4739.85843
10146.19 42.9689   10173 44.779910212.4446.3336210227.69 47.621110250.9748.32555
#Mann= 3 , 0 , 0
9749.024    0.12       09749.024    0.12       010250.97    0.12       0
#XS Ineff= 2 , 0
       0                               0
Bank Sta=9749.024,10250.97
Exp/Cntr=0.3,0.1

Type RM Length L Ch R = 1 ,543.0569,98.835100,98.835100,98.835100
XS GIS Cut Line= 6
1192782.68439269627601.5181950651192824.63798062627662.891583608
1192869.39379302627720.3146513971193018.66129582627882.403069713
1193060.87272292627938.9654867231193095.61980134627992.441000973
#Sta/Elev= 30
9749.033110.67979756.455 108.4339760.429106.6875  9780.395.816899792.222 88.1431
9803.62683.160619836.52462.145049853.16253.204699865.64146.08018 9873.9641.89304
9890.637 34.55749894.75932.815949903.46130.068249912.24327.777399935.48123.70284
9942.97923.887329959.647 23.47219973.70622.611499983.07821.6282510002.3120.84272
10048.0220.4178210053.7421.0167310087.3829.4893810104.71 34.200910125.8437.83775
10154.4940.0809410162.6841.2999510179.0641.6126410191.1542.7208610250.9642.82776
#Mann= 3 , 0 , 0
9749.033    0.12       09749.033    0.12       010250.96    0.12       0
#XS Ineff= 2 , 0
       0                               0
Bank Sta=9749.033,10250.96
Exp/Cntr=0.3,0.1

Type RM Length L Ch R = 1 ,444.2218,98.835100,98.835100,98.835100
XS GIS Cut Line= 6
1192717.24330942627651.7183764351192771.55586073627731.957306114
1192840.58326937627825.4964717521192885.94648165627890.614760891
1192962.94621499627993.8124966851193008.12274405628060.683487439
#Sta/Elev= 30
9749.01693.870889767.10889.23312  9774.488.521269782.95588.660549791.95987.14835
9797.81285.731369802.76483.759049806.72581.369299815.37173.916299826.53465.35293
9842.38154.433359850.43350.004999883.38433.861719895.28529.126129927.58721.70567
9956.44717.67974 9972.5418.2183910001.0416.9554510012.4717.5337110073.25 15.4039
10081.4414.1042410085.5315.1115710110.0928.3106610114.1830.0534310118.2831.03008
10155.1233.3470510195.2134.9079210219.7835.32609 10234.834.4786410250.9834.46491
#Mann= 3 , 0 , 0
9749.016    0.12       09749.016    0.12       010250.98    0.12       0
#XS Ineff= 2 , 0
       0                               0
Bank Sta=9749.016,10250.98
Exp/Cntr=0.3,0.1