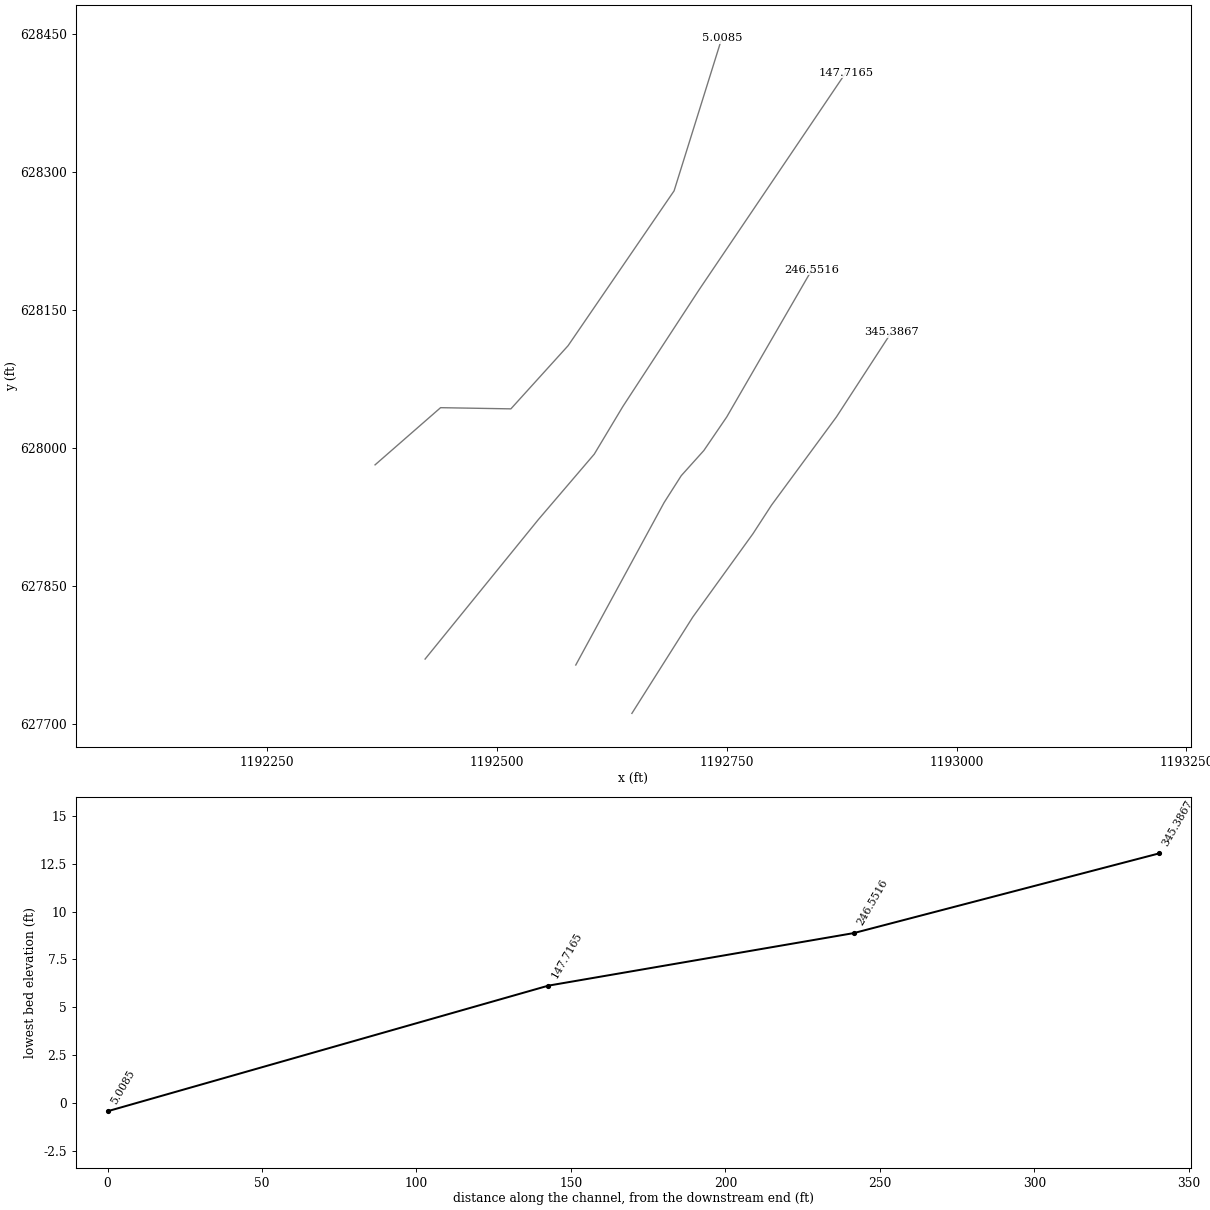
HEC-RAS study 386_ras.prj: 386

--- 386_ras.g01 (geometry) --- (continued)

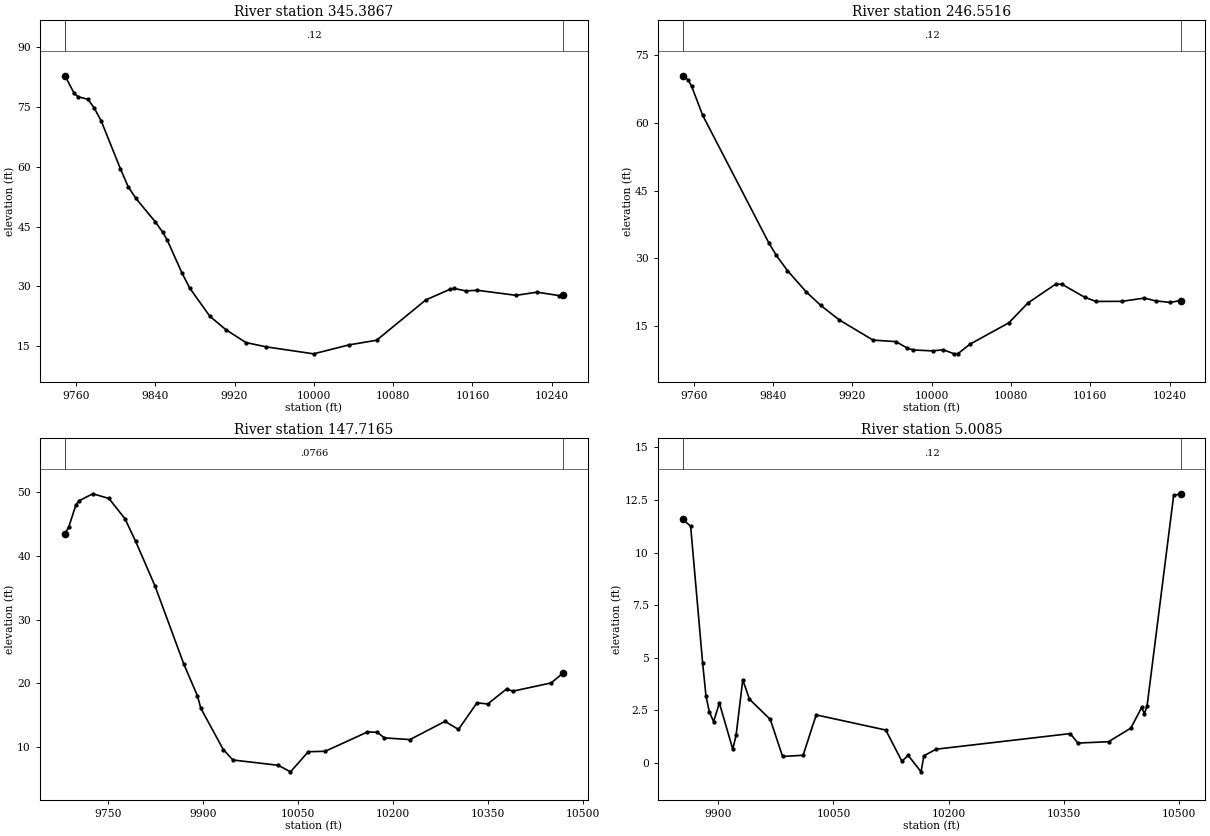
Type RM Length L Ch R = 1 ,345.3867,98.835100,98.835100,98.835100
XS GIS Cut Line= 6
1192646.88285067627711.3040921561192713.17694539627816.154354193
1192778.57402489627906.7295498921192798.71746144627937.751172086
1192869.31014551628033.6798337731192929.29452303628125.972390655
#Sta/Elev= 30
9749.032 82.86589758.36778.427269762.24877.610349772.25676.942479778.39574.82571
9785.53871.535059804.94659.502819812.70955.037859820.47252.100979839.88146.25557
9847.64443.561029852.06441.652739867.05233.328739874.88929.528579895.12222.47575
9911.30819.096949931.54215.866599951.77514.798689999.77213.0356610035.5715.28769
10063.3216.4509110112.9726.5802610137.4129.2505810141.46 29.4663 10153.228.84253
10164.9428.9951410204.0627.72437 10225.1 28.528310247.1127.6739810250.97 27.7885
#Mann= 3 , 0 , 0
9749.032    0.12       09749.032    0.12       010250.97    0.12       0
#XS Ineff= 2 , 0
       0                               0
Bank Sta=9749.032,10250.97
Exp/Cntr=0.3,0.1

Type RM Length L Ch R = 1 ,246.5516,98.835100,98.835100,98.835100
XS GIS Cut Line= 6
1192585.84444008627763.8994493941192681.89138136627940.524837208
1192700.55056315627969.8008428181192725.12770063627997.159564334
1192749.98760879628033.6095411471192842.72067542628193.914145694
#Sta/Elev= 30
9749.04170.38854 9754.1569.510769757.86868.085239769.02561.645899835.96333.32674
  9843.430.633179854.55627.28016 9873.1522.654699888.03219.597429906.88616.37553
9940.82311.915039963.87111.578939975.20810.167239981.3129.72962910001.61 9.52559
10011.459.79997610022.718.87681410026.688.94266110038.59  11.01410077.85 15.7447
10096.9920.12087 10125.324.3378510131.4524.26174 10154.421.3773610165.6820.46778
10191.9820.4905910214.5221.2153310225.7920.5877410240.82 20.258310250.9520.67598
#Mann= 3 , 0 , 0
9749.041    0.12       09749.041    0.12       010250.95    0.12       0
#XS Ineff= 2 , 0
       0                               0
Bank Sta=9749.041,10250.95
Exp/Cntr=0.3,0.1

Type RM Length L Ch R = 1 ,147.7165,142.708000,142.708000,142.708000
XS GIS Cut Line= 6
1192421.98473248627770.3797498351192545.07162464627921.970974892
1192605.96724495627993.2318071721192637.06288087 628045.05786705
1192719.98457664628172.0317136791192879.34971064628407.840286016
#Sta/Elev= 30
9682.12443.484599688.03444.495259699.46647.994679704.67148.63788 9726.0749.71232
9751.42648.980189776.78345.804069793.68842.260819824.38235.229479869.75923.01431
9891.175 18.0577 9896.6616.074919932.0119.6294139947.2777.99213610018.857.158441
10038.146.13530110066.239.286716   100939.35580310159.6112.3824510175.2812.33783
10186.1611.4585410226.6811.1895210282.1214.0479110303.3412.7815810332.6416.96097
10349.4316.7643310379.51 19.135310389.0318.7727810449.8220.0741310467.8321.57449
#Mann= 3 , 0 , 0
9682.124  0.0766       09682.124  0.0766       010467.83  0.0766       0
#XS Ineff= 2 , 0
       0                10060.51       0
Bank Sta=9682.124,10467.83
Exp/Cntr=0.3,0.1

Type RM Length L Ch R = 1 ,  5.0085,0.000000,0.000000,0.000000
XS GIS Cut Line= 6
1192367.56736964627981.5709437131192438.82820195 628043.76221554
1192515.27164021628042.4665640441192577.46291202628111.136093348
1192692.77589518628279.5707878771192744.60195503  628445.4141794
#Sta/Elev= 30
9853.85711.574139863.97211.255129879.629 4.748799883.9843.1771659888.3382.425675
 9893.911.9671129901.4022.8487039918.8580.6569219923.1751.3130229931.8843.953896
9940.5933.0318079967.7012.0710469983.7180.31093110010.460.36678210027.512.286511
 10118.11.56614810139.06  0.0863 10147.40.35801710164.07-0.4201410167.710.340687
10183.67 0.6562510358.391.39776810368.240.94727210408.251.01129510437.281.658772
10451.382.64148310454.912.33890610458.432.71929810493.0112.7138610501.9812.79565
#Mann= 3 , 0 , 0
9853.857    0.12       09853.857    0.12       010501.98    0.12       0
#XS Ineff= 2 , 0
       0 9972.22        10052.18       0
Bank Sta=9853.857,10501.98
Exp/Cntr=0.3,0.1